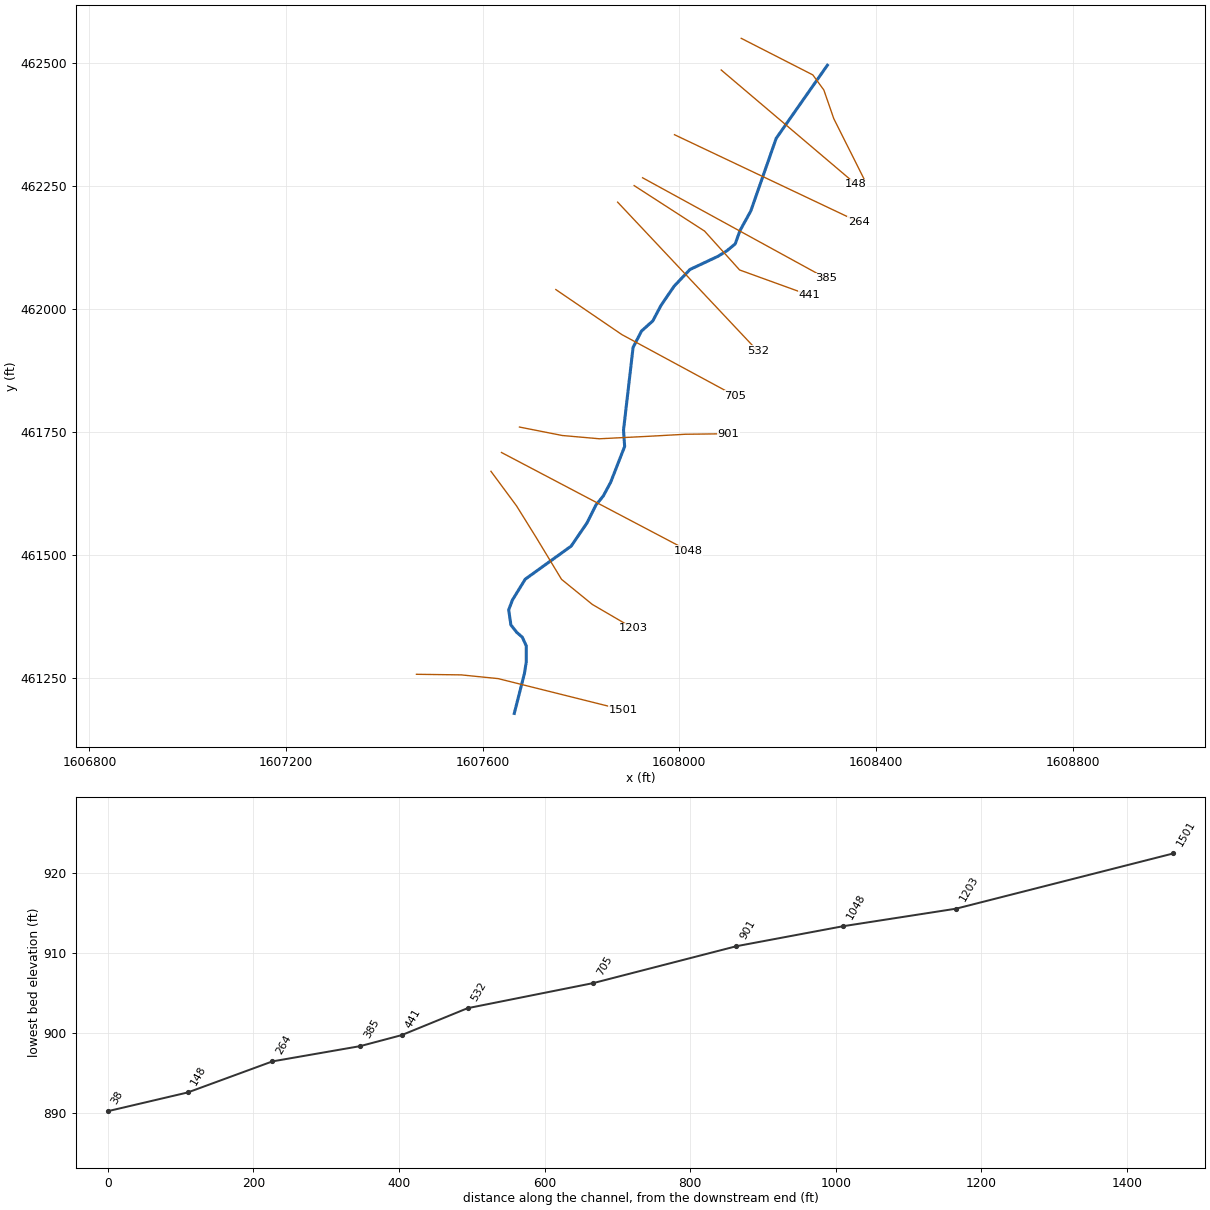
--- LngRunT1.prj (project) ---

Proj Title=LngRunT1
Current Plan=p01
Default Exp/Contr=0.3,0.1
English Units
Geom File=g01
Flow File=f01
Plan File=p01
Y Axis Title=Elevation
X Axis Title(PF)=Main Channel Distance
X Axis Title(XS)=Station
BEGIN DESCRIPTION:
---------- MODELED AS PART OF WVEM CTP PROGRAM, 2025----------
Stream Name: Long Run Tributary 1
Flood Zone: AFH
Marshall County, WV
HEC-RAS Version: RAS 6.6
Vertical Datum: NAVD88
Projection: NAD 1983 StatePlane West Virginia N FIPS 4701 (US Feet)
Terrain: 1-meter West Virginia FEMA R3 South Central (collected 2018-2019)
Land Use: 2024 NLCD
Hydrologic Method:
Duda et al., "Estimation of magnitude and frequency of floods for rural, unregulated streams in and near Virginia and West Virginia." September 8, 2025.
Additional Model Notes:
None
END DESCRIPTION:
DSS File=dss
DSS Export Rating Curves= 0
DSS Export Rating Curve Sorted= 0
DSS Export Volume Flow Curves= 0
DXF OffsetX= 0
DXF OffsetY= 0
DXF ScaleX= 1
DXF ScaleY= 10

--- LngRunT1.p01 (plan) ---

Plan Title=Floodplain
Program Version=6.60
Short Identifier=Floodplain
Geom File=g01
Flow File=f01
Subcritical Flow
K Sum by GR= 0
Std Step Tol= 0.01
Critical Tol= 0.01
Num of Std Step Trials= 20
Max Error Tol= 0.3
Flow Tol Ratio= 0.001
Split Flow NTrial= 30
Split Flow Tol= 0.02
Split Flow Ratio= 0.02
Log Output Level= 0
Friction Slope Method= 1
Unsteady Friction Slope Method= 2
Unsteady Bridges Friction Slope Method= 1
Parabolic Critical Depth
Global Vel Dist= 0 , 0 , 0
Global Log Level= 0
CheckData=True
Encroach Param=-1 ,0,0, 0
Flow Ratio Tolerance=0.1
Flow Ratio Min Ratio=0.5
Flow Ratio Max Ratio=4
Flow Ratio Max Iterations= 10
Computation Interval=1MIN
Output Interval=1HOUR
Instantaneous Interval=1HOUR
Mapping Interval=1HOUR
Computation Time Step Use Courant=        0
Computation Time Step Use Time Series=    0
Computation Time Step Count To Double=0
Computation Time Step Max Doubling=0
Computation Time Step Max Halving=0
Computation Time Step Residence Courant=0
Run HTab= 0
Run UNet= 0
Run Sediment= 0
Run PostProcess= 0
Run WQNet= 0
Run RASMapper=-1
UNET Theta= 1
UNET Theta Warmup= 1
UNET ZTol= 0.02
UNET ZSATol= 0.02
UNET MxIter= 20
UNET Max Iter WO Improvement= 0
UNET MaxInSteps= 0
UNET DtIC= 0
UNET DtMin= 0
UNET MaxCRTS= 20
UNET WFStab= 2
UNET SFStab= 1
UNET WFX= 1
UNET SFX= 1
UNET Gravity=32.17405
UNET 1D Methodology=Finite Difference
UNET DSS MLevel= 4
UNET Pardiso=0
UNET DZMax Abort= 100
UNET Use Existing IB Tables=-1
UNET Froude Reduction=False
UNET Froude Limit= 0.8
UNET Froude Power= 4
UNET D1 Cores= 0
UNET WindReference=Eulerian
UNET WindDragFormulation=Hsu (1988)
UNET D2 Coriolis=0
UNET D2 Cores= 0
UNET D2 Theta= 1
UNET D2 Theta Warmup= 1
UNET D2 Z Tol= 0.01
UNET D2 Volume Tol= 0.01
UNET D2 Max Iterations= 20
UNET D2 Advanced Convergence=0
UNET D2 WS Max Tol=0.15
UNET D2 WS RMS Tol=0.002
UNET D2 WS Stall Tol=1
UNET D2 Equation= 0
UNET D2 RampUpFraction=0.1
UNET D2 TimeSlices= 1
UNET D2 Turbulence Formulation=None
UNET D2 Eddy Viscosity=0.3
UNET D2 Transverse Eddy Viscosity=0.1
UNET D2 Smagorinsky Mixing=0.05
UNET D2 BCVolumeCheck=0
UNET D2 Cores=0
UNET D2 SolverType=PARDISO (Direct)
UNET D2 Minimum Iterations= 3
UNET D2 Maximum Iterations= 30
UNET D2 Restart Number= 10
UNET D2 Relaxation Coeff=1.3
UNET D2 SOR Precondition Iterations= 10
UNET D2 ILUT Maximum Fill= 8
UNET D2 ILUT Tolerance=1E-08
UNET D2 Convergence Tolerance=0.00001
PS Theta= 1
PS WS Tol= 0.01
PS Volume Tol= 0.01
PS Max Iterations= 20
PS Equation= 0
PS Advance Time Step=-1
PS Target Courant=0.9
PS Time Slices= 1
PS Iterate With 2D=0
PS Project Initial WSE from DS=-1
PS Ramp Up Initial WSE from US=-1
PS Cores=0
UNET D1D2 MaxIter= 0
UNET D1D2 ZTol=0.01
UNET D1D2 QTol=0.1
UNET D1D2 MinQTol=1
DSS File=dss
Write IC File= 0
Write IC File at Fixed DateTime=0
Write IC File at Sim End=0
Echo Input=False
Echo Parameters=False
Echo Output=False
Write Detailed= 0
HDF Write Warmup=0
HDF Write Time Slices=0
HDF Flush=0
HDF Compression= 1
HDF Chunk Size= 1
HDF Spatial Parts= 1
HDF Use Max Rows=0
HDF Fixed Rows= 1
Calibration Method= 0
Calibration Iterations= 20
Calibration Max Change=0.05
Calibration Tolerance=0.2
Calibration Maximum=1.5
Calibration Minimum=0.5
Calibration Optimization Method= 1
WQ AD Non Conservative
WQ ULTIMATE=-1
WQ Max Comp Step=1HOUR
WQ Output Interval=15MIN
WQ Output Selected Increments= 0
WQ Create Restart=0
WQ Fixed Restart=0
WQ System Summary=0
WQ Write To DSS=0
Sorting and Armoring Iterations= 10
XS Update Threshold= 0.02
Bed Roughness Predictor= 0
Processes Affected by Predictor=Sediment Only
Hydraulics Update Threshold= 0.02
Energy Slope Method= 1
Volume Change Method= 1
Sediment Retention Method= 0
Sediment TS Multiplier= 1
Warm Up Method= 0
XS Weighting Method= 0
Number of US Weighted Cross Sections= 1
Number of DS Weighted Cross Sections= 1
Upstream XS Weight=0
Main XS Weight=1
Downstream XS Weight=0
Number of DS XS's Weighted with US Boundary= 1
Upstream Boundary Weight= 1
Weight of XSs Associated with US Boundary= 0
Number of US XS's Weighted with DS Boundary= 1
Downstream Boundary Weight= 0.5
Weight of XSs Associated with DS Boundary= 0.5
Percentile Method= 0
Sediment Output Level= 3
Mass or Volume Output= 0
Output Increment Type= 1
Profile and TS Output Increment= 1
Transport Output Increment 1
XS Output Flag= 0
XS Output Increment= 10
Read HDF5 Sediment Hotstart= 0
Sediment Hotstart Type= 0
Write Gradation File= 0
Read Gradation Hotstart= 0
Write HDF5 File= 1
Write Binary Output= 1
Write DSS Sediment File= 0
DSS Sediment Output Type= 1
SV Curve= 0
Specific Gage Flag= 0
Subcell Erosion Methods= 0
Subcell Deposition Methods= 0
Advection Scheme= 1
Matrix Solver= 0
Implicit Weighting Factor= 1
Maximum Outer Loop Convergence Iterations= 5
Convergence Maximum Absolute= 0.001
Convergence RMSE= 0.0001
Grain Fractions Max Abs Error= 0.001
Max Subgrid Regions= 1
Max Subgrid Length Scale= 3.402823E+38
Initial Layer Thickness= 3
Min Layer Thickness= 0.1
Max Layer Thickness= 6
Number of Layers= 5

--- LngRunT1.f01 (steady flow) ---

Flow Title=Flow
Program Version=6.60
Number of Profiles= 1
Profile Names=P100yr
River Rch & RM=LngRunT1,Main            ,1501
     771
Boundary for River Rch & Prof#=LngRunT1,Main            , 1
Up Type= 0
Dn Type= 3
Dn Slope=0.033
DSS Import GetInterval= 0
DSS Import GetPeak= 0
DSS Import FillOption= 0

--- LngRunT1.g01 (geometry) ---

Geom Title=Geometry
Program Version=6.60

River Reach=LngRunT1        ,Main
Reach XY= 30
1607664.24910647461177.8935588151607685.00201772461259.439327478
1607688.66703664461282.8949892221607688.66703664461315.146893233
1607680.44723681461333.0507288131607669.60933197461342.267573893
1607657.37740105461357.7065193951607652.89377419461388.434228284
1607660.32642873461408.197520124 1607686.5457432461450.841838474
1607779.92505622461518.0493745651607811.99356164 461565.00662972
1607830.31865622461601.6564908031607845.20740597461619.981585398
 1607860.0964838461647.4687351441607888.72897246461720.768457308
1607886.43862273461753.9823016381607905.90872814461922.342201144
1607923.08815572461955.5560454731607945.99427789461976.171489805
1607962.45815572462007.3095508961607989.30127789462046.679222807
1608021.51282763462080.6804671441608078.05654427462107.295093291
1608096.53468562462118.6854678171608113.65311052462132.864457785
1608123.37035533462159.8522867671608145.34641001 462199.79285924
1608196.88780497 462347.321994231608301.03917147 462496.14026615

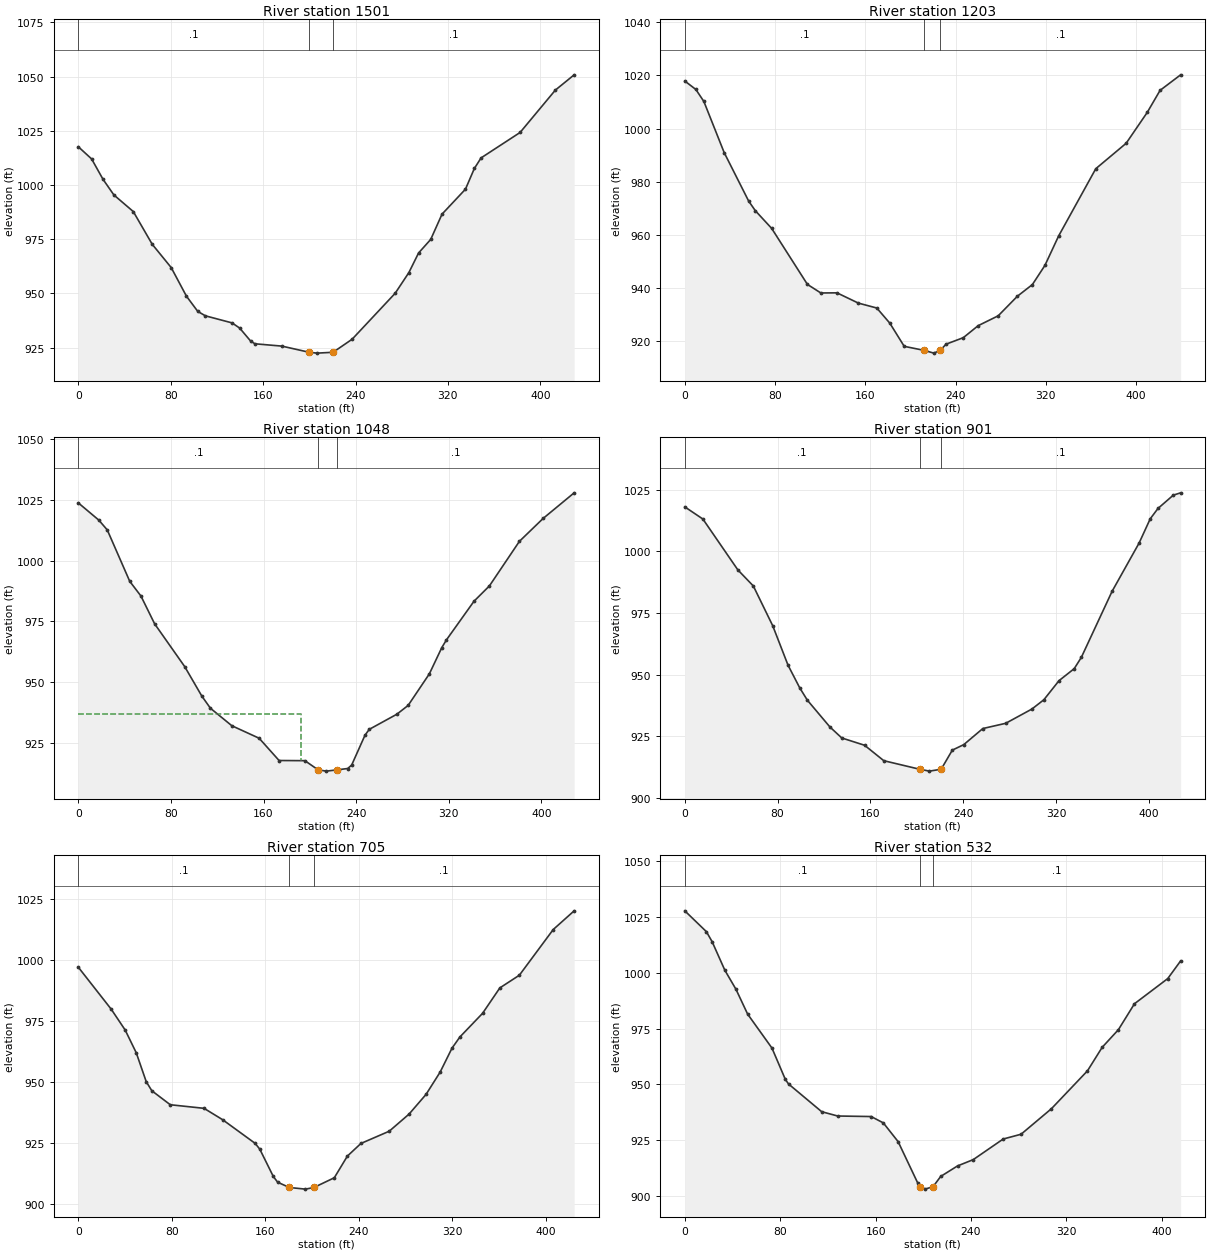
Type RM Length L Ch R = 1 ,1501    ,301.3,298.6,291.6
XS GIS Cut Line= 6
1607465.27345459461257.3727305831607556.28738017461256.184412763
1607631.66124517461248.5653335011607728.67515875461224.310132667
1607801.43616809461206.1208645851607886.32313742461184.898138002
#Sta/Elev= 30
       0 1017.63    11.5 1012.03    21.4  1002.6    30.8   995.4    47.6  987.74
      64  972.63    80.4  961.91    93.6  948.71   103.4  941.69     110  939.64
   133.1  936.38   139.7  933.98   149.1  928.05   152.9  926.74   176.2  925.67
   199.9  922.82   206.7  922.43  220.57  922.82   237.1  928.86   274.3  950.03
   286.2   959.6   294.6  968.64   305.1  974.89   314.9  986.55   335.2  998.08
   342.9 1007.64   348.7  1012.5   382.5 1024.24     413 1043.77   429.3 1050.83
#Mann= 3 ,0,0
       0      .1       0   199.9    .045       0  220.57      .1       0
Bank Sta=199.9,220.57
XS Rating Curve= 0 ,0
Exp/Cntr(USF)=0,0
Exp/Cntr=0.3,0.1

Type RM Length L Ch R = 1 ,1203    ,149.8,155,158
XS GIS Cut Line= 6
1607616.76757418461670.2908679991607668.89804734461599.843502343
1607708.48556659461536.1822123381607760.34930801 461450.53244926
1607823.06571801461399.4465934191607905.86640543461351.093999833
#Sta/Elev= 30
       0 1017.89     9.8 1014.71    16.9  1010.2    34.9  990.97    56.6  972.73
    62.5  969.11      77  962.45   108.7  941.37   120.6  938.15   134.9   938.2
   153.9  934.33   170.2  932.49   181.7  926.81   194.5  918.07  211.77916.5925
   220.8  915.52  226.45916.5904   231.6  918.89   246.9  921.34     260  925.84
   277.8  929.56   294.8  936.92   308.1  941.31   319.2  948.51   331.4  959.63
   364.3   984.9   391.2  994.46   409.9 1006.08   421.3 1014.38   439.5 1020.22
#Mann= 3 ,-1,0
       0      .1       0  211.77    .045       0  226.45      .1       0
Bank Sta=211.77,226.45
XS Rating Curve= 0 ,0
Exp/Cntr(USF)=0,0
Exp/Cntr=0.3,0.1

Type RM Length L Ch R = 1 ,1048    ,139.5,146.6,149.5
XS GIS Cut Line= 2
1607638.27391024461708.4980145171608017.29327268461509.054358071
#Sta/Elev= 30
       0  1023.7    17.7 1016.62      25 1012.58    44.4  991.44    54.1  985.37
    65.9  973.95    91.9  956.33   106.7  944.19   114.1  939.21   132.6  932.01
   156.2  926.86   173.4   917.7   195.7  917.63   207.2  913.84   214.2  913.33
   223.1  913.82   232.7  914.41   236.1  915.82   247.6  928.09   251.3  930.52
   275.2  936.76   284.9  940.38   303.2  953.34     314  964.19     318  967.35
   341.8  983.25   355.1  989.55     381 1007.88   401.5 1017.31   428.3 1027.85
#Mann= 3 ,0,0
       0      .1       0   207.2    .045       0   223.1      .1       0
#XS Ineff= 2 , 0
          192.76  936.95
Permanent Ineff=
       F       F
Bank Sta=207.2,223.1
XS Rating Curve= 0 ,0
Exp/Cntr(USF)=0,0
Exp/Cntr=0.3,0.1

Type RM Length L Ch R = 1 ,901     ,203.8,196.6,192.8
XS GIS Cut Line= 6
1607674.73793067461760.2598481771607762.05501325461743.060407504
1607837.53124025461736.4111425881607937.42178851461741.447877929
1608012.31238675461745.6168328371608099.94869442461746.651607677
#Sta/Elev= 30
       0 1018.05    15.6 1013.11    45.7   992.5    59.1  985.93    75.8  969.81
      89   953.8      99  944.68   105.6  939.64   125.1  928.74   135.3  924.29
     155  921.32   171.5  915.07  202.48911.5906   210.9  910.83  220.98911.5925
   230.6  919.35   240.5  921.59   256.9  928.11   276.6  930.23   299.2  936.02
   309.5  939.78   322.6  947.55   335.7  952.42   341.8  956.97   368.3  983.77
   391.6 1003.37   401.2 1013.21   407.9 1017.42   421.1 1022.81   427.4 1023.75
#Mann= 3 ,-1,0
       0      .1       0  202.48    .045       0  220.98      .1       0
Bank Sta=202.48,220.98
XS Rating Curve= 0 ,0
Exp/Cntr(USF)=0,0
Exp/Cntr=0.3,0.1

Type RM Length L Ch R = 1 ,705     ,175.2,172.7,170.2
XS GIS Cut Line= 4
1607748.75332843462039.8967290331607821.04780327461990.604832869
1607883.01487093461948.3542612011608113.40655438461823.821724041
#Sta/Elev= 30
       0   997.2    28.2  979.96    40.1  971.45    49.6   962.1    58.1   950.3
    62.9  946.56    78.7  940.82   107.6  939.35   123.5  934.69   151.3     925
   155.3  922.62   166.9   911.4   170.6  909.06   180.6  906.89   194.4  906.22
  201.68   906.9   219.1  910.88   230.3  919.77   241.9  924.95   266.1  929.96
   283.1  936.99   297.6  945.05   309.7  954.21   319.8  963.99   326.6  968.61
     346   978.3   360.8  988.73   377.5  993.93   406.5 1012.67   424.4 1020.33
#Mann= 3 ,0,0
       0      .1       0   180.6    .045       0  201.68      .1       0
Bank Sta=180.6,201.68
XS Rating Curve= 0 ,0
Exp/Cntr(USF)=0,0
Exp/Cntr=0.3,0.1

Type RM Length L Ch R = 1 ,532     ,89,90.6,90.1
XS GIS Cut Line= 2
1607874.50732957462217.6796415071608159.41336167461914.849057716
#Sta/Elev= 30
       0 1027.77    18.1 1018.44    22.9 1013.96    33.6 1001.14    42.9  992.63
    52.7  981.49    73.1  966.27    84.3  952.26      87  950.19   114.8  937.77
   128.2  935.84   156.3   935.6   166.5  932.75   178.9  924.35   195.2  905.98
  197.54904.1714   201.4  903.08  208.21904.1723   214.6  908.77   228.7  913.47
   241.9   916.3     267  925.53     282  927.67   307.5  939.13   337.7  956.09
     350  966.61   363.6   974.5   377.1  986.14     405  997.41   415.8 1005.33
#Mann= 3 ,-1,0
       0      .1       0  197.54    .045       0  208.21      .1       0
Bank Sta=197.54,208.21
XS Rating Curve= 0 ,0
Exp/Cntr(USF)=0,0
Exp/Cntr=0.3,0.1

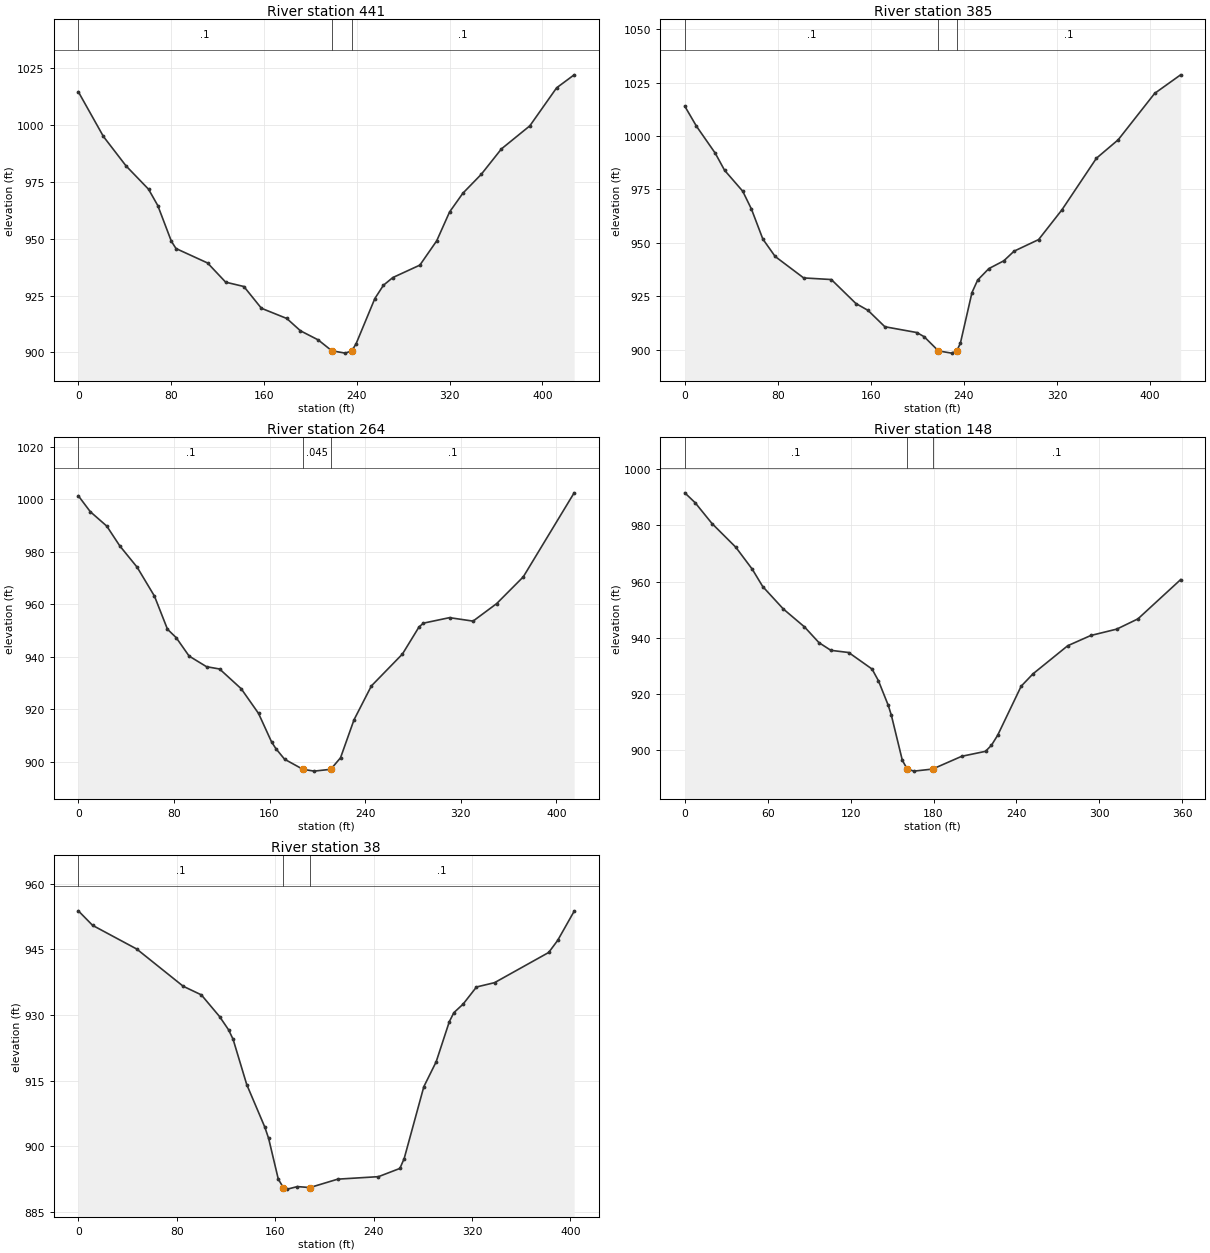
Type RM Length L Ch R = 1 ,441     ,53.2,56.8,58.8
XS GIS Cut Line= 4
1607908.11585286462251.3314699391608051.28201135462158.858387023
1608122.58655722462079.7549064551608264.08151542462028.504764116
#Sta/Elev= 30
       0 1014.55    21.6  994.92    41.1  981.99    60.5  971.74    68.5  964.54
    80.2  948.86    84.2  945.66   111.4  939.32     127  930.89   142.7  928.98
   157.8  919.42   179.7  914.93   191.5  909.51   206.8  905.51  218.52900.7345
   230.1  899.71  235.74900.7368   239.4  903.79   255.6   923.7     263  929.54
   271.1  932.92   294.4  938.38   308.9  949.04     320  961.72   331.5  969.99
   347.3  978.26   364.7  989.44   389.2  999.58   412.3 1016.29   427.4 1021.99
#Mann= 3 ,-1,0
       0      .1       0  218.52    .045       0  235.74      .1       0
Bank Sta=218.52,235.74
XS Rating Curve= 0 ,0
Exp/Cntr(USF)=0,0
Exp/Cntr=0.3,0.1

Type RM Length L Ch R = 1 ,385     ,120.4,120.6,120.9
XS GIS Cut Line= 2
1607925.20532234462267.2917624591608299.10486678462062.476117871
#Sta/Elev= 30
       0 1013.98      10 1004.63    26.2  991.95    34.2  983.97    49.8  974.17
    57.3   965.8    67.1  951.76    77.7   943.6   102.2  933.56     126   932.8
   147.1  921.58   157.5  918.37     172   910.7   199.5  907.98   205.8  906.03
  218.09899.3719   229.4  898.34  233.73899.3722   236.9  902.89   246.9   926.7
   251.8  932.56   261.4  937.92   274.3  941.58   283.1  946.09   304.2  951.51
   324.2  965.41   353.9  989.61   372.6  998.24     404 1019.99   426.3 1028.67
#Mann= 3 ,-1,0
       0      .1       0  218.09    .045       0  233.73      .1       0
Bank Sta=218.09,233.73
XS Rating Curve= 0 ,0
Exp/Cntr(USF)=0,0
Exp/Cntr=0.3,0.1

Type RM Length L Ch R = 1 ,264     ,119.2,116.2,114.9
XS GIS Cut Line= 2
1607990.08029578462354.8802684831608365.04494901462177.245234668
#Sta/Elev= 30
       0 1001.27      10  995.22    23.8  989.73    34.7  982.19    49.2  974.08
    63.7  963.07    74.6  950.45    81.9  947.25    92.7  940.24   107.3  936.19
   118.2  935.32   136.3   927.8   150.8   918.4   161.7  907.55   165.3     905
   172.6  900.96  187.92897.1258   197.3  896.43   211.2897.1254   219.4  901.51
   230.7  915.99   245.2  928.86   271.2  941.01   285.1  951.34   288.8  952.78
   310.6  954.87   330.3  953.55     350   960.2   372.3  970.39   414.9  1002.4
#Mann= 3 ,-1,0
       0      .1       0  187.92    .045       0   211.2      .1       0
Bank Sta=187.92,211.2
XS Rating Curve= 0 ,0
Exp/Cntr(USF)=0,0
Exp/Cntr=0.3,0.1

Type RM Length L Ch R = 1 ,148     ,112.6,110.1,107.3
XS GIS Cut Line= 2
1608085.12873645462486.4971620521608358.71399906462254.421387559
#Sta/Elev= 30
       0  991.57     7.5  988.05    19.7  980.64    36.9  972.22    48.9  964.34
    56.4  958.22    71.3  950.24    86.6  943.87    97.1  938.26   105.7  935.53
   118.6  934.75   135.5  928.87   140.1  924.74   147.2     916   149.5  912.39
   157.4  896.43  160.95893.2825   165.8  892.55  179.29893.2819   200.4  897.83
   217.6  899.59   221.9  901.75   226.4  905.31   243.4  922.76     252  927.18
   277.1  937.17   293.8  940.81   312.6  943.08   327.9  946.72   358.8  960.69
#Mann= 3 ,-1,0
       0      .1       0  160.95    .045       0  179.29      .1       0
Bank Sta=160.95,179.29
XS Rating Curve= 0 ,0
Exp/Cntr(USF)=0,0
Exp/Cntr=0.3,0.1

Type RM Length L Ch R = 1 ,38      ,,,
XS GIS Cut Line= 5
1608125.89895102462550.8911022521608271.44152144 462476.54823314
1608293.88627556462445.8351483251608314.08416531462387.582705997
1608376.85408977462262.416103229
#Sta/Elev= 30
       0  953.82    11.6   950.5    47.4   945.1    85.3  936.57     100  934.61
   114.8  929.66   122.1  926.64   125.8  924.47   136.9  914.11   151.6  904.38
   154.7   901.8   162.6  892.45   166.7  890.56     170   890.2   178.1  890.78
  188.29  890.56   210.9  892.48     244  893.05   261.4  894.93   264.9  897.18
   280.9  913.63   290.9   919.3   301.6  928.48   305.3  930.54   312.8  932.49
   323.7  936.41   338.4   937.4   382.4   944.3   389.7  947.06   403.1  953.73
#Mann= 3 ,-1,0
       0      .1       0   166.7    .045       0  188.29      .1       0
Bank Sta=166.7,188.29
XS Rating Curve= 0 ,0
Exp/Cntr(USF)=0,0
Exp/Cntr=0.3,0.1
LCMann Table=0

Chan Stop Cuts=-1
Use User Specified Reach Order=0
Composite Channel Slope=5